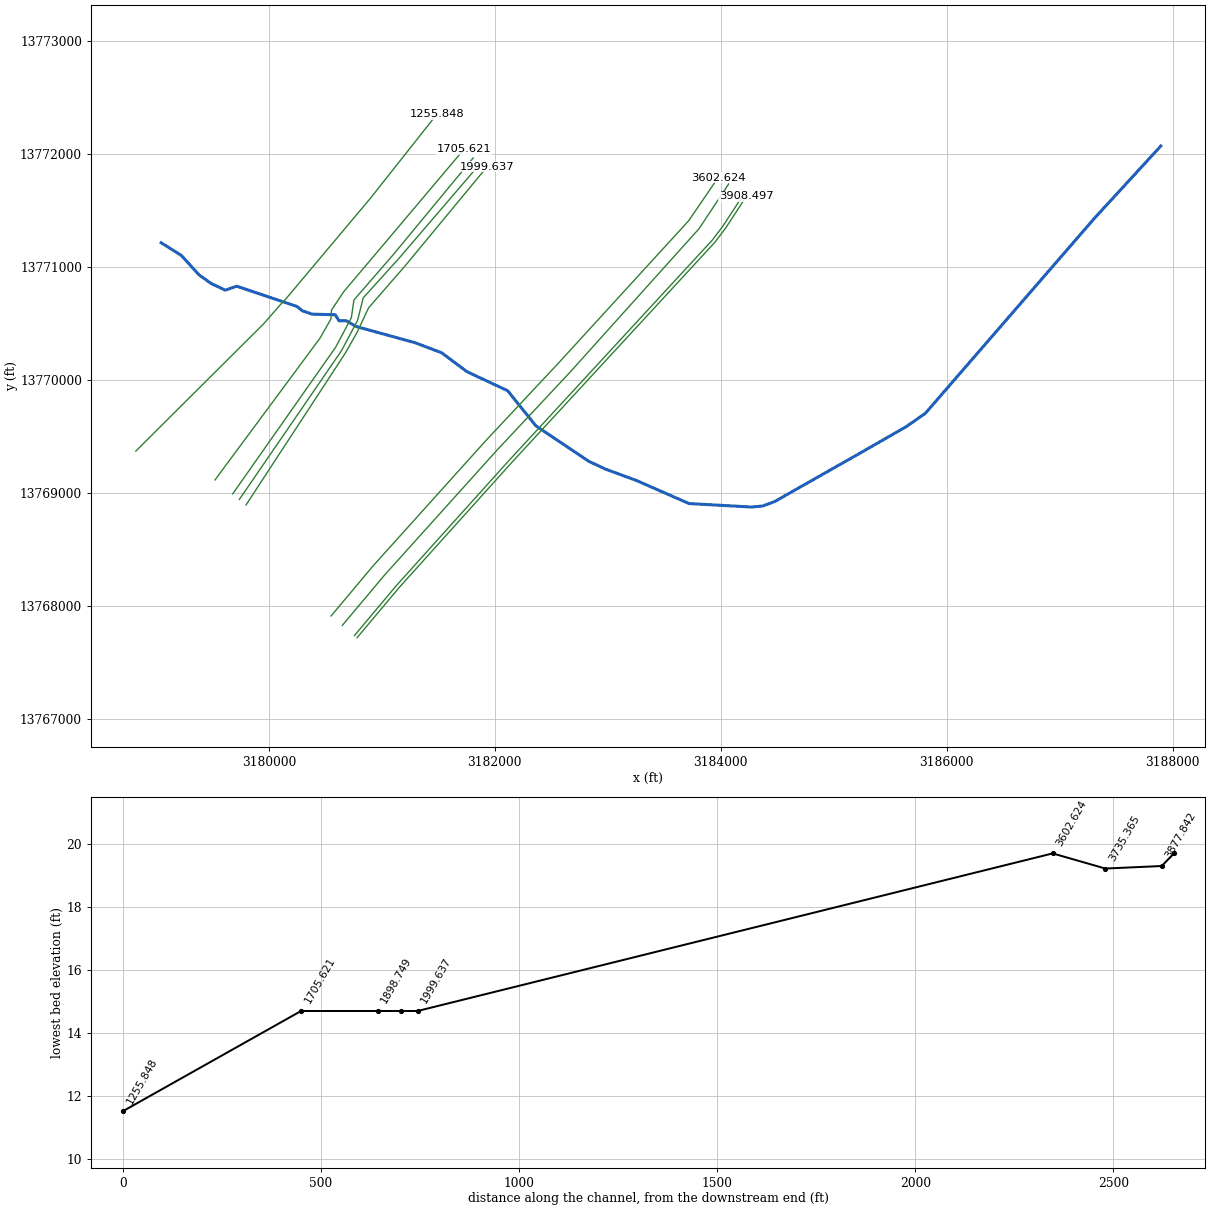
--- A119_02_00.prj (project) ---

Proj Title=A119-02-00
Current Plan=p02
Default Exp/Contr=.3,.1
English Units
Geom File=g01
Geom File=g02
Flow File=f02
Flow File=f01
Plan File=p01
Plan File=p02
Y Axis Title=Elevation
X Axis Title(PF)=Main Channel Distance
X Axis Title(XS)=Station
BEGIN DESCRIPTION:
Clear Creek Basin
Turkey Creek Tributary 0.16
A119-02-00
Flood Hazard Model
10, 2, 1 & 0.2% Events
Filename: A119_02_00.prj
Prepared by: Perry Vaught	Date: 4-15-04
Reviewed by: __________	Date:
Status (FINAL)
END DESCRIPTION:
DSS Export Rating Curves= 0
DSS Export Rating Curve Sorted= 0
DSS Export Volume Flow Curves= 0
DXF OffsetX= 0
DXF OffsetY= 0
DXF ScaleX= 1
DXF ScaleY= 10

--- A119_02_00.p02 (plan) ---

Plan Title=Floodway
Version=Version 3.0.1  Mar 2001
Short Identifier=Floodway0607
Geom File=g02
Flow File=f02
Subcritical Flow
K Sum by GR= 0
Std Step Tol= 0.003
Critical Tol= 0.003
Num of Std Step Trials= 20
Max Error Tol= 0.1
Flow Tol Ratio= 0.001
Split Flow NTrial= 30
Split Flow Tol= 0.02
Split Flow Ratio= 0.02
Log Output Level= 0
Friction Slope Method= 0
Unsteady Friction Slope Method= 2
Secant Critical Depth
Global Vel Dist= 0 , 0 , 0
Global Log Level= 0
CheckData=True
Encroach Param=-1 ,0,0, 2
Encroach River=A119-02-00
Encroach Reach=A119-02-00_0013
Encroach Node=3908.497
       1 4980.96 5019.04
Encroach Node=3877.842
       1 4980.96 5019.04
Encroach Node=3806
       1 4980.96 5019.04
Encroach Node=3735.365
       1 4980.96 5019.04
Encroach Node=3602.624
       1    4963    5027
Encroach Node=1999.637
       1 4952.15 5047.85
Encroach Node=1959.076
       1 4952.15 5047.85
Encroach Node=1928
       1 4952.15 5047.85
Encroach Node=1898.749
       1 4952.15 5047.85
Encroach Node=1705.621
       1 4952.15    5064
Encroach Node=1255.848
       1 4965.85 5034.15
Computation Interval=1HOUR
Output Interval=1HOUR
Run HTab= 0
Run UNet= 0
Run PostProcess= 0
UNET Theta= 1
UNET ZTol= 0.02
UNET ZSATol= 0.1
UNET MxIter= 20
UNET MaxInSteps= 20
UNET DtIC= 0
UNET DtMin= 0
UNET MaxCRTS= 20
UNET WFStab= 2
UNET SFStab= 1
UNET WFX= 1
UNET SFX= 1
UNET Convert EG Bridges=-1
UNET Use Existing IB Tables=-1
Instantaneous Interval=1HOUR
Write IC File= 0
IC Time=0
Write Velocity= 0
Write Detailed= 0

--- A119_02_00.p01 (plan) ---

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Plan Title=FEMA Effective June 2007
Short Identifier=FEMAeff0607
Geom File=g01
Flow File=f01

--- A119_02_00.f02 (steady flow) ---

Flow Title=Floodway
Version=Version 3.0.1  Mar 2001
Number of Profiles= 2
Profile Names=1PCT_100yr, 1PCTFloodway_100yrFW
River Rch & RM=A119-02-00,A119-02-00_0013      ,3908.497
     606     606
River Rch & RM=A119-02-00,A119-02-00_0013      ,3602.624
     675     675
River Rch & RM=A119-02-00,A119-02-00_0013      ,1999.637
     689     689
River Rch & RM=A119-02-00,A119-02-00_0013      ,1705.621
     710     710
Boundary for River Rch & Prof#=A119-02-00,A119-02-00_0013      , 1
Up Type= 0
Dn Type= 3
Dn Slope=.007
DSS Import GetInterval= 0
DSS Import GetPeak= 0
DSS Import FillOption= 0

--- A119_02_00.f01 (steady flow) ---

Flow Title=FEMA Effective June 2007
Version=Version 3.0.1  Mar 2001
Number of Profiles= 4
Profile Names=10PCT_10yr, 2PCT_50yr, 1PCT_100yr, 0.2PCT_500yr
River Rch & RM=A119-02-00,A119-02-00_0013      ,3908.497
     329     511     606     888
River Rch & RM=A119-02-00,A119-02-00_0013      ,3602.624
     367     569     675     990
River Rch & RM=A119-02-00,A119-02-00_0013      ,1999.637
     374     580     689    1009
River Rch & RM=A119-02-00,A119-02-00_0013      ,1705.621
     386     598     710    1040
Boundary for River Rch & Prof#=A119-02-00,A119-02-00_0013      , 1
Up Type= 0
Dn Type= 3
Dn Slope=.007
Boundary for River Rch & Prof#=A119-02-00,A119-02-00_0013      , 2
Up Type= 0
Dn Type= 3
Dn Slope=.007
Boundary for River Rch & Prof#=A119-02-00,A119-02-00_0013      , 3
Up Type= 0
Dn Type= 3
Dn Slope=.007
Boundary for River Rch & Prof#=A119-02-00,A119-02-00_0013      , 4
Up Type= 0
Dn Type= 3
Dn Slope=.007
DSS Import GetInterval= 0
DSS Import GetPeak= 0
DSS Import FillOption= 0

--- A119_02_00.g02 (geometry) ---

Geom Title=A119-02-00 June 2007 (Floodway)
Version=Version 3.0.1  Mar 2001

River Reach=A119-02-00,A119-02-00_0013
Reach XY= 30
     3187896.323    13772068.561     3187307.988    13771428.233
       3185812.5       13769703.     3185646.966    13769586.606
       3185236.5    13769351.272        3184480.       13768922.
      3184370.75    13768881.001     3184270.535    13768872.395
      3183719.75       13768903.        3183252.    13769107.999
     3182984.407    13769206.241     3182831.166    13769277.388
       3182362.5       13769592.        3182114.       13769902.
      3181754.75       13770070.      3181528.75       13770238.
      3181296.75       13770326.     3180771.184    13770470.778
     3180685.534    13770520.987     3180620.557    13770520.987
     3180588.069     13770574.15     3180381.327    13770580.056
     3180295.676    13770609.591     3180248.421    13770647.986
       3179715.5       13770827.      3179612.72    13770791.988
     3179488.988    13770851.858     3179381.222    13770927.694
     3179225.559    13771099.322     3179046.491       13771212.

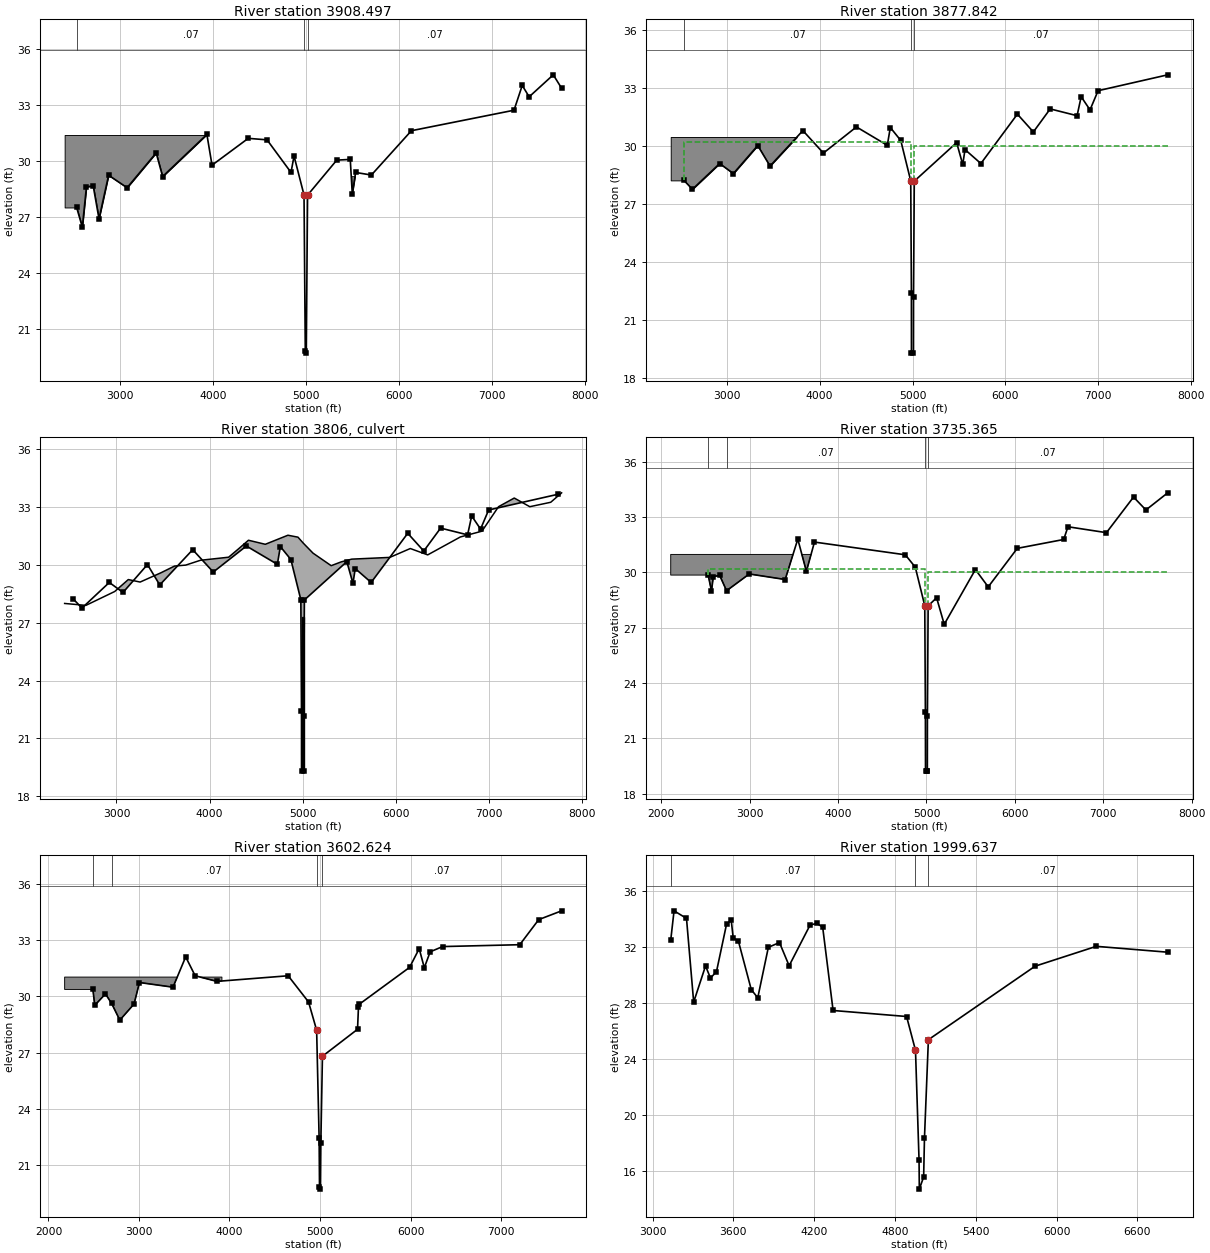
Type RM Length L Ch R = 1 ,3908.497,30.05,30.66,30.03
XS GIS Cut Line= 6
     3180780.527    13767715.172     3181150.376    13768156.002
      3182143.63    13769259.456     3183947.926    13771215.352
     3184042.866    13771340.674     3184226.669    13771622.005
#Sta/Elev= 30
 2536.18   27.52 2597.32   26.46 2641.77   28.63 2714.56   28.67 2776.63   26.91
 2879.89   29.25 3078.71   28.58 3391.26   30.45 3460.72   29.18 3936.62   31.44
 3991.79   29.79 4381.33   31.23 4583.24   31.15    4841    29.4 4873.61   30.28
 4980.96   28.19 4994.55   19.83 5005.24    19.7 5019.04   28.18 5332.68   30.06
 5478.07    30.1 5499.66   28.26 5535.75    29.4 5705.11   29.26 6135.52   31.64
 7238.71   32.74 7327.15   34.07 7401.68   33.46 7660.87   34.64 7750.62   33.92
#Mann= 3 ,-1 , 0
 2536.18     .07       0 4980.96    .045       0 5019.04     .07       0
#Block Obstruct= 2 ,-1
 2407.11 3936.63   31.41    5460    5640    29.2
Bank Sta=4980.96,5019.04
XS Rating Curve= 0
Exp/Cntr=.5,.3

Type RM Length L Ch R = 1 ,3877.842,140.24,142.48,140.15
XS GIS Cut Line= 6
     3180757.545    13767734.454     3181127.748    13768175.707
     3182121.548    13769279.766     3183924.837    13771234.556
     3184018.323    13771357.957     3184201.554    13771638.414
#Sta/Elev= 30
 2537.87   28.22 2629.14   27.76    2923   29.09 3070.29   28.57 3332.81   30.02
 3465.03   28.96 3819.12   30.79 4040.14   29.63 4395.85   30.98 4728.64   30.03
 4760.74   30.95 4873.61   30.28 4980.96   28.19 4988.03   22.43 4988.51    19.3
 5010.46   19.33 5010.94   22.18 5019.04   28.18 5475.37   30.17  5540.9   29.04
 5565.53   29.81 5736.31   29.09  6129.6   31.64 6301.75   30.72  6482.9   31.91
 6772.62   31.56 6816.74   32.54 6911.97   31.86 6998.95   32.85 7748.73   33.67
#Mann= 3 ,-1 , 0
 2537.87     .07       0 4980.96    .045       0 5019.04     .07       0
#XS Ineff= 2 , 0
       0 4980.96    30.2 5019.04       0      30
Permanent Ineff=
       F       F
#Block Obstruct= 2 ,-1
 2395.55 3878.63   30.46    5600    5770    29.1
Bank Sta=4980.96,5019.04
XS Rating Curve= 0
Exp/Cntr=.5,.3

Type RM Length L Ch R = 2 ,3806    ,,,
BEGIN DESCRIPTION:
2351
END DESCRIPTION:
Bridge Culvert--1,0,-1,-1, 0
Deck Dist Width WeirC Skew NumUp NumDn MinLoCord MaxHiCord MaxSubmerge Is_Ogee
12,93,2.6,0, 30, 30, , , .95, 0, 0,0,,
    2443    2671    2981    3127    3254    3477    3624    3744    3902    4205
    4313    4418    4599    4842    4950    5007    5112    5307    5416    5528
    5937    6157    6344    6695    6927    7105    7274    7441    7666    7783
      28    27.9   28.62   29.24   29.11   29.59   29.94   29.99   30.24    30.4
   30.84   31.28   31.07   31.54   31.44   31.13   30.61   29.96   30.16    30.3
   30.39   30.85   30.52   31.45   31.75   33.02   33.47   33.02   33.25   33.74
                                                                                
                                                                                
                                                                                
    2443    2671    2981    3127    3254    3477    3624    3744    3902    4205
    4313    4418    4599    4842    4950    5007    5112    5307    5416    5528
    5937    6157    6344    6695    6927    7105    7274    7441    7666    7783
      28    27.9   28.62   29.24   29.11   29.59   29.94   29.99   30.24    30.4
   30.84   31.28   31.07   31.54   31.44   31.13   30.61   29.96   30.16    30.3
   30.39   30.85   30.52   31.45   31.75   33.02   33.47   33.02   33.25   33.74
                                                                                
                                                                                
                                                                                
Multiple Barrel Culv=2,8,10,119,.012,.5,1,8,1,19.319,19.248, 2,Culvert #1  , 0 ,0
  4994.5  4994.5  5005.5  5005.5
Culvert Bottom n=.012
BC Design=,, 0 ,, 0 ,,,,,,

Type RM Length L Ch R = 1 ,3735.365,130.23,132.74,130.14
XS GIS Cut Line= 6
     3180650.292    13767824.437     3181022.149     13768267.66
     3182018.498    13769374.546     3182661.034    13770060.216
     3183808.851    13771337.043     3184069.952    13771731.804
#Sta/Elev= 30
 2531.01   29.85 2568.42   28.98 2589.27   29.77 2661.47   29.83 2738.92      29
 2995.99   29.91 3402.13   29.61 3544.74    31.8 3641.79   30.05 3733.14   31.64
 4760.74   30.95 4873.61   30.28 4980.96   28.19 4988.01   22.45 4989.38   19.25
 5004.65   19.22  5010.1   19.22 5010.92   22.19 5019.04   28.18 5114.83   28.62
 5201.16   27.18 5553.79   30.15 5698.63   29.21 6027.69    31.3 6552.57   31.78
 6600.65   32.47 7035.98   32.15 7342.46   34.08 7482.49   33.38 7728.89   34.31
#Mann= 4 ,-1 , 0
 2531.01     .15       0 2738.92     .07       0 4980.96    .045       0
 5019.04     .07       0
#XS Ineff= 2 , 0
       0 4980.96    30.2 5019.04       0      30
Permanent Ineff=
       F       F
#Block Obstruct= 1 ,-1
 2107.27 3859.36   30.97
Bank Sta=4980.96,5019.04
XS Rating Curve= 0
Exp/Cntr=.5,.3

Type RM Length L Ch R = 1 ,3602.624,1540.46,1602.99,1655.12
XS GIS Cut Line= 6
     3180550.701    13767907.993     3180924.092    13768353.046
     3181922.809    13769462.556      3182566.13    13770149.069
     3183717.039    13771407.387      3183975.52     13771786.09
#Sta/Elev= 30
 2490.96   30.37 2511.38   29.52 2629.83   30.13  2698.1   29.62 2788.48   28.73
 2945.63   29.59 3005.57   30.74 3376.03   30.49 3516.06   32.11 3620.79    31.1
 3861.08    30.8  4648.4    31.1 4873.61    29.7    4963   28.19  4990.4   22.42
 4994.55   19.83 5005.24    19.7 5009.43   22.19    5027    26.8 5414.73   28.24
 5425.24   29.44 5434.17   29.58 5990.22   31.55 6096.03   32.55 6152.42   31.53
 6217.38   32.38 6354.74   32.66  7207.2   32.76 7416.54    34.1 7669.57   34.57
#Mann= 4 ,-1 , 0
 2490.96     .15       0  2698.1     .07       0    4963    .045       0
    5027     .07       0
#Block Obstruct= 1 ,-1
 2178.78 3916.57   31.03
Bank Sta=4963,5027
XS Rating Curve= 0
Exp/Cntr=.3,.1

Type RM Length L Ch R = 1 ,1999.637,40.73,40.56,95.36
XS GIS Cut Line= 6
     3179798.193    13768891.228       3180677.4    13770235.923
     3180781.497    13770419.227     3180882.201    13770634.572
     3181209.947    13771011.537     3181933.471    13771886.557
#Sta/Elev= 30
 3134.67   32.51 3159.36   34.61 3251.78   34.07  3305.1   28.08 3393.22   30.67
 3429.63    29.8 3474.48   30.26  3549.7   33.68 3584.03   33.93 3598.64   32.67
 3637.31   32.44 3732.86   28.97 3780.94   28.39 3859.57      32 3942.15   32.34
 4013.87   30.68 4169.86    33.6  4220.3   33.71 4262.98   33.44 4340.29   27.48
 4885.95   27.05 4952.15   24.63 4978.51   16.78 4980.54    14.7 5012.66   15.57
 5018.74   18.35 5047.85   25.39 5840.29   30.65 6294.59   32.07 6824.75   31.65
#Mann= 3 ,-1 , 0
 3134.67     .07       0 4952.15    .045       0 5047.85     .07       0
Bank Sta=4952.15,5047.85
XS Rating Curve= 0
Exp/Cntr=.5,.3

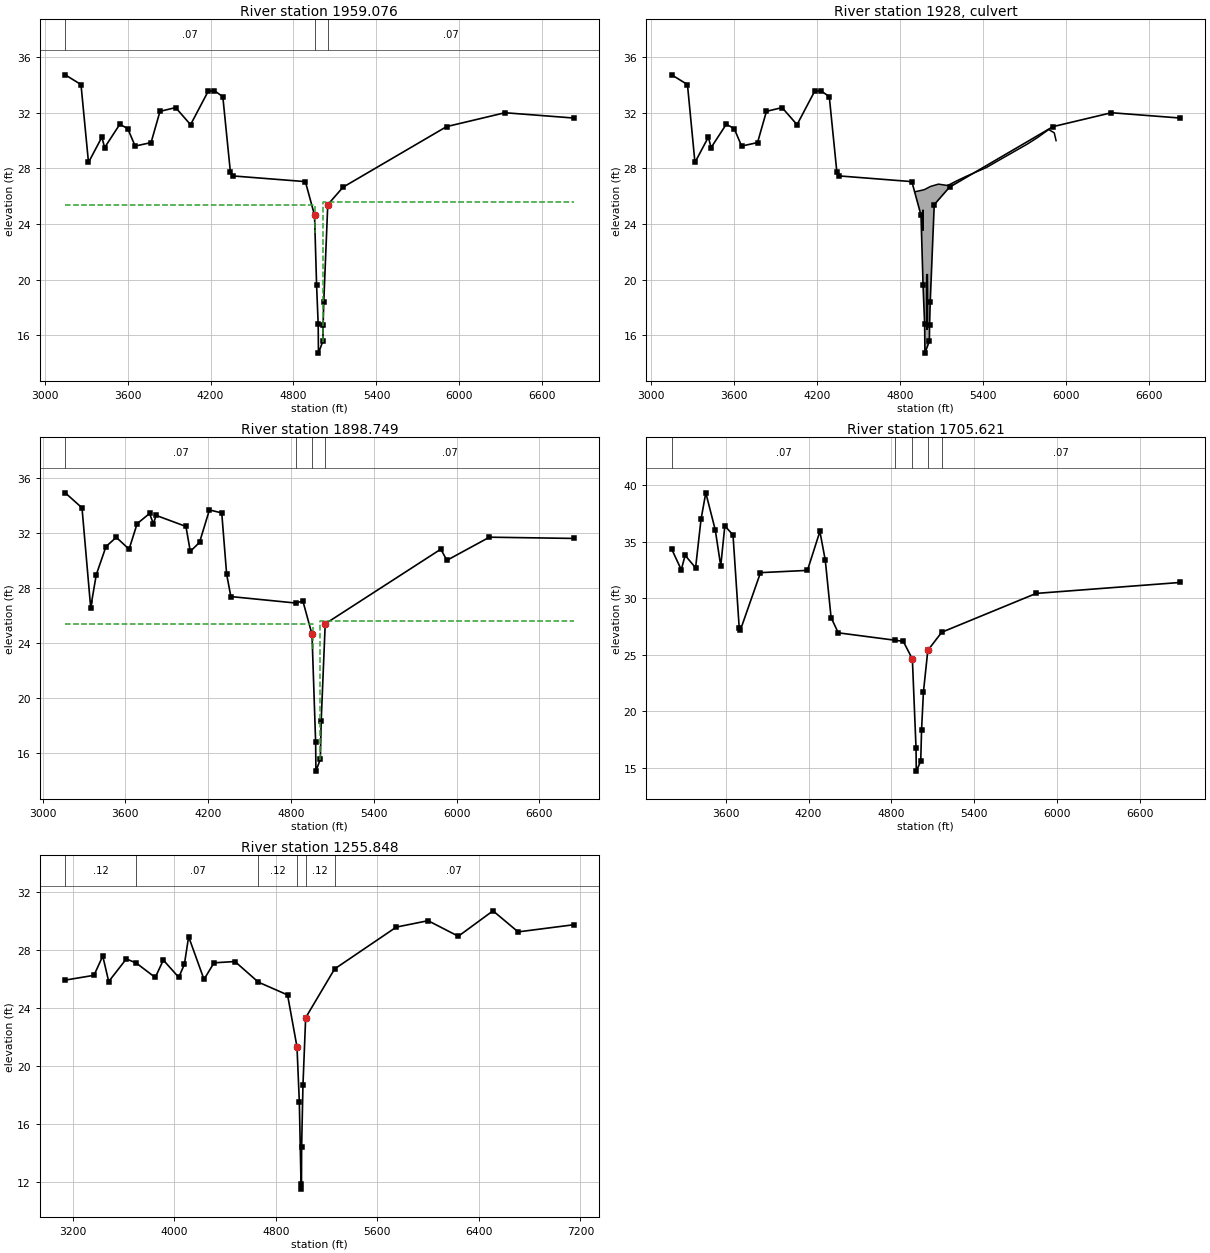
Type RM Length L Ch R = 1 ,1959.076,61.1,60.33,62.01
XS GIS Cut Line= 6
     3179738.893    13768939.746     3180643.003    13770256.354
     3180784.789    13770523.245     3180835.582    13770724.024
     3181158.543    13771081.589     3181866.623    13771907.447
#Sta/Elev= 30
 3148.89   34.74 3263.01   34.04 3317.24   28.43 3414.04   30.25 3434.15    29.5
 3543.76   31.18 3601.13   30.87 3654.66   29.61 3769.87   29.86 3834.27   32.11
 3947.41   32.38 4055.62   31.15 4183.69   33.57  4228.3   33.59 4288.79   33.17
 4343.41   27.75 4360.96   27.46 4885.95   27.05 4952.15   24.63 4967.03   19.59
 4978.51   16.78 4980.54    14.7 5012.66   15.57 5014.27   16.73 5018.74   18.35
 5047.85   25.39 5158.44   26.65 5907.02   31.01  6329.4   32.01 6825.37   31.63
#Mann= 3 ,-1 , 0
 3148.89     .07       0 4952.15    .045       0 5047.85     .07       0
#XS Ineff= 2 , 0
       0    4956    25.4    5010       0    25.6
Permanent Ineff=
       F       F
Bank Sta=4952.15,5047.85
XS Rating Curve= 0
Exp/Cntr=.5,.3

Type RM Length L Ch R = 2 ,1928    ,,,
BEGIN DESCRIPTION:
ACCESS RD OFF BEAMER RD
END DESCRIPTION:
Bridge Culvert--1,0,-1,-1, 0
Deck Dist Width WeirC Skew NumUp NumDn MinLoCord MaxHiCord MaxSubmerge Is_Ogee
19,32,2.6,0, 17, 17, , , .95, 0, 0,0,,
    4908    4959    4978    5020    5078    5146    5205    5279    5357    5424
    5504    5606    5722    5793    5876    5916    5929
   26.32   26.43   26.48    26.7   26.87   26.77   27.08   27.43   27.77   28.06
   28.52    29.1   29.76   30.21    30.8   30.56      30
       0       0       0       0       0       0       0       0       0       0
       0       0       0       0       0       0       0
    4908    4959    4978    5020    5078    5146    5205    5279    5357    5424
    5504    5606    5722    5793    5876    5916    5947
   26.32   26.43   26.48    26.7   26.87   26.77   27.08   27.43   27.77   28.06
   28.52    29.1   29.76   30.21    30.8   30.56      30
       0       0       0       0       0       0       0       0       0       0
       0       0       0       0       0       0       0
Culvert=1,1.5,,32,.0112,.5,1,1,1,23.523,4967,22.86,4967,Culvert #2  , 0 ,19
Culvert Bottom n=.0112
Multiple Barrel Culv=1,4,,32,.012,.5,1,1,1,16.4,16.7, 2,Culvert #1  , 0 ,19
  4993.5  4993.5  4998.5  4998.5
Culvert Bottom n=.012
BC Design=,, 0 ,, 0 ,,,,,,

Type RM Length L Ch R = 1 ,1898.749,164.36,193.13,127.31
XS GIS Cut Line= 6
     3179679.593    13768988.264     3180591.407    13770287.001
      3180730.39    13770548.563     3180752.919      13770704.8
     3181104.716    13771110.424     3181808.131    13771961.761
#Sta/Elev= 30
  3164.3    34.9 3285.94   33.81 3348.83   26.57 3389.38   28.96 3459.75      31
 3534.02   31.67 3626.93   30.81 3685.42   32.66 3775.36    33.4  3802.8   32.66
  3823.3   33.26 4038.83   32.46 4070.49   30.65 4137.24    31.3 4209.03   33.66
 4298.31   33.44 4333.73      29 4364.25   27.37 4835.25    26.9 4885.95   27.05
 4952.15   24.63 4978.51   16.78 4980.54    14.7 5012.66   15.57 5018.74   18.35
 5047.85   25.39 5885.47   30.81 5929.16      30 6237.58   31.68 6846.76   31.59
#Mann= 4 ,-1 , 0
  3164.3     .07       0 4835.25     .12       0 4952.15    .045       0
 5047.85     .07       0
#XS Ineff= 2 , 0
       0    4956    25.4    5010       0    25.6
Permanent Ineff=
       F       F
#Block Obstruct= 1 ,-1
    3330    3380    27.1
Bank Sta=4952.15,5047.85
XS Rating Curve= 0
Exp/Cntr=.5,.3

Type RM Length L Ch R = 1 ,1705.621,505.32,449.77,394.01
XS GIS Cut Line= 6
     3179523.257    13769112.255     3180453.818    13770368.727
     3180549.608    13770537.402     3180554.211    13770615.403
     3180662.412    13770777.712     3181728.749    13772041.143
#Sta/Elev= 30
 3207.69   34.37 3277.18   32.54 3305.27   33.81 3381.04   32.71 3420.32   36.99
 3454.95   39.35 3523.54   36.07 3563.25   32.87    3593   36.42 3652.22   35.62
  3697.2   27.37 3705.84    27.2 3851.44   32.28 4191.68   32.48 4281.87   35.93
 4320.97   33.38 4363.01    28.3 4415.14   26.95 4828.69   26.29 4885.95    26.2
 4952.15   24.63 4978.51   16.78 4980.54    14.7 5012.66   15.57 5018.74   18.35
 5032.18   21.69    5064   25.39 5164.75      27 5849.19   30.44 6891.78   31.41
#Mann= 5 ,-1 , 0
 3207.69     .07       0 4828.69     .12       0 4952.15    .045       0
    5064     .12       0 5164.75     .07       0
Bank Sta=4952.15,5064
XS Rating Curve= 0
Exp/Cntr=.3,.1

Type RM Length L Ch R = 1 ,1255.848,856.81,1255.85,901.48
XS GIS Cut Line= 6
     3178822.399    13769367.465     3179956.073    13770496.493
     3180105.457    13770667.637     3180152.559    13770717.101
      3180899.19    13771605.723     3181489.378    13772351.809
#Sta/Elev= 30
 3138.57   25.91 3365.48   26.24 3434.64   27.57 3481.49   25.81 3620.38   27.37
 3699.61   27.08 3848.49   26.09    3912   27.29 4033.85    26.1  4078.2      27
 4111.58    28.9 4232.78   25.96  4311.7    27.1 4476.74   27.19 4661.38   25.77
  4891.5   24.89 4965.85   21.31 4984.37    17.5 4998.55   11.52 5001.17   11.84
 5002.34    14.4  5012.8   18.66 5034.15   23.32 5262.49   26.68  5748.8   29.56
 5999.27      30 6237.71   28.93 6511.23   30.68 6708.94   29.23 7145.96   29.72
#Mann= 6 ,-1 , 0
 3138.57     .12       0 3699.61     .07       0 4661.38     .12       0
 4965.85    .045       0 5034.15     .12       0 5262.49     .07       0
Bank Sta=4965.85,5034.15
XS Rating Curve= 0
Exp/Cntr=.3,.1

Chan Stop Cuts=-1

--- A119_02_00.g01 (geometry) ---

Geom Title=A119-02-00 June 2007
Version=Version 3.0.1  Mar 2001

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
River Reach=A119-02-00    ,A119-02-00_0013
Reach XY= 30
     3187896.323    13772068.561     3187307.988    13771428.233
       3185812.5       13769703.     3185646.966    13769586.606
       3185236.5    13769351.272        3184480.       13768922.
      3184370.75    13768881.001     3184270.535    13768872.395
      3183719.75       13768903.        3183252.    13769107.999
     3182984.407    13769206.241     3182831.166    13769277.388
       3182362.5       13769592.        3182114.       13769902.
      3181754.75       13770070.      3181528.75       13770238.
      3181296.75       13770326.     3180771.184    13770470.778
     3180685.534    13770520.987     3180620.557    13770520.987
     3180588.069     13770574.15     3180381.327    13770580.056
     3180295.676    13770609.591     3180248.421    13770647.986
       3179715.5       13770827.      3179612.72    13770791.988
     3179488.988    13770851.858     3179381.222    13770927.694
     3179225.559    13771099.322     3179046.491       13771212.

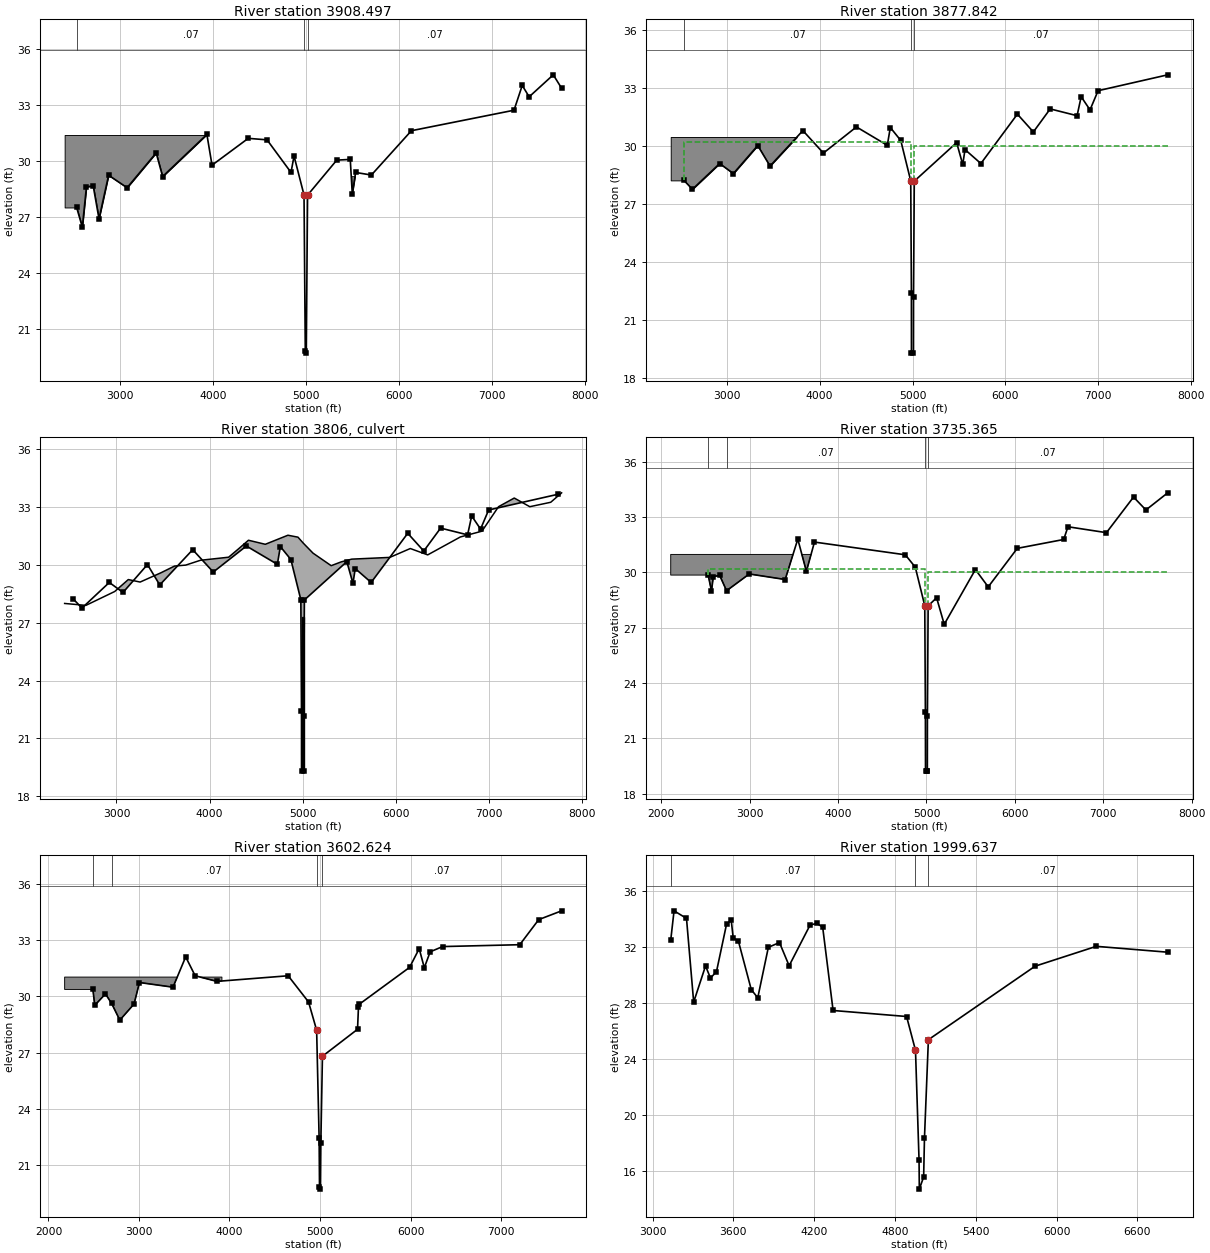
Type RM Length L Ch R = 1 ,3908.497,30.05,30.66,30.03
XS GIS Cut Line= 6
     3180780.527    13767715.172     3181150.376    13768156.002
      3182143.63    13769259.456     3183947.926    13771215.352
     3184042.866    13771340.674     3184226.669    13771622.005
#Sta/Elev= 30
 2536.18   27.52 2597.32   26.46 2641.77   28.63 2714.56   28.67 2776.63   26.91
 2879.89   29.25 3078.71   28.58 3391.26   30.45 3460.72   29.18 3936.62   31.44
 3991.79   29.79 4381.33   31.23 4583.24   31.15    4841    29.4 4873.61   30.28
 4980.96   28.19 4994.55   19.83 5005.24    19.7 5019.04   28.18 5332.68   30.06
 5478.07    30.1 5499.66   28.26 5535.75    29.4 5705.11   29.26 6135.52   31.64
 7238.71   32.74 7327.15   34.07 7401.68   33.46 7660.87   34.64 7750.62   33.92
#Mann= 3 ,-1 , 0
 2536.18     .07       0 4980.96    .045       0 5019.04     .07       0
#Block Obstruct= 2 ,-1
 2407.11 3936.63   31.41    5460    5640    29.2
Bank Sta=4980.96,5019.04
XS Rating Curve= 0
Exp/Cntr=.5,.3

Type RM Length L Ch R = 1 ,3877.842,140.24,142.48,140.15
XS GIS Cut Line= 6
     3180757.545    13767734.454     3181127.748    13768175.707
     3182121.548    13769279.766     3183924.837    13771234.556
     3184018.323    13771357.957     3184201.554    13771638.414
#Sta/Elev= 30
 2537.87   28.22 2629.14   27.76    2923   29.09 3070.29   28.57 3332.81   30.02
 3465.03   28.96 3819.12   30.79 4040.14   29.63 4395.85   30.98 4728.64   30.03
 4760.74   30.95 4873.61   30.28 4980.96   28.19 4988.03   22.43 4988.51    19.3
 5010.46   19.33 5010.94   22.18 5019.04   28.18 5475.37   30.17  5540.9   29.04
 5565.53   29.81 5736.31   29.09  6129.6   31.64 6301.75   30.72  6482.9   31.91
 6772.62   31.56 6816.74   32.54 6911.97   31.86 6998.95   32.85 7748.73   33.67
#Mann= 3 ,-1 , 0
 2537.87     .07       0 4980.96    .045       0 5019.04     .07       0
#XS Ineff= 2 , 0
       0 4980.96    30.2 5019.04       0      30
Permanent Ineff=
       F       F
#Block Obstruct= 2 ,-1
 2395.55 3878.63   30.46    5600    5770    29.1
Bank Sta=4980.96,5019.04
XS Rating Curve= 0
Exp/Cntr=.5,.3

Type RM Length L Ch R = 2 ,3806    ,,,
BEGIN DESCRIPTION:
2351
END DESCRIPTION:
Bridge Culvert--1,0,-1,-1, 0
Deck Dist Width WeirC Skew NumUp NumDn MinLoCord MaxHiCord MaxSubmerge Is_Ogee
12,93,2.6,0, 30, 30, , , .95, 0, 0,0,,
    2443    2671    2981    3127    3254    3477    3624    3744    3902    4205
    4313    4418    4599    4842    4950    5007    5112    5307    5416    5528
    5937    6157    6344    6695    6927    7105    7274    7441    7666    7783
      28    27.9   28.62   29.24   29.11   29.59   29.94   29.99   30.24    30.4
   30.84   31.28   31.07   31.54   31.44   31.13   30.61   29.96   30.16    30.3
   30.39   30.85   30.52   31.45   31.75   33.02   33.47   33.02   33.25   33.74
                                                                                
                                                                                
                                                                                
    2443    2671    2981    3127    3254    3477    3624    3744    3902    4205
    4313    4418    4599    4842    4950    5007    5112    5307    5416    5528
    5937    6157    6344    6695    6927    7105    7274    7441    7666    7783
      28    27.9   28.62   29.24   29.11   29.59   29.94   29.99   30.24    30.4
   30.84   31.28   31.07   31.54   31.44   31.13   30.61   29.96   30.16    30.3
   30.39   30.85   30.52   31.45   31.75   33.02   33.47   33.02   33.25   33.74
                                                                                
                                                                                
                                                                                
Multiple Barrel Culv=2,8,10,119,.012,.5,1,8,1,19.319,19.248, 2,Culvert #1  , 0 ,0
  4994.5  4994.5  5005.5  5005.5
Culvert Bottom n=.012
BC Design=,, 0 ,, 0 ,,,,,,

Type RM Length L Ch R = 1 ,3735.365,130.23,132.74,130.14
XS GIS Cut Line= 6
     3180650.292    13767824.437     3181022.149     13768267.66
     3182018.498    13769374.546     3182661.034    13770060.216
     3183808.851    13771337.043     3184069.952    13771731.804
#Sta/Elev= 30
 2531.01   29.85 2568.42   28.98 2589.27   29.77 2661.47   29.83 2738.92      29
 2995.99   29.91 3402.13   29.61 3544.74    31.8 3641.79   30.05 3733.14   31.64
 4760.74   30.95 4873.61   30.28 4980.96   28.19 4988.01   22.45 4989.38   19.25
 5004.65   19.22  5010.1   19.22 5010.92   22.19 5019.04   28.18 5114.83   28.62
 5201.16   27.18 5553.79   30.15 5698.63   29.21 6027.69    31.3 6552.57   31.78
 6600.65   32.47 7035.98   32.15 7342.46   34.08 7482.49   33.38 7728.89   34.31
#Mann= 4 ,-1 , 0
 2531.01     .15       0 2738.92     .07       0 4980.96    .045       0
 5019.04     .07       0
#XS Ineff= 2 , 0
       0 4980.96    30.2 5019.04       0      30
Permanent Ineff=
       F       F
#Block Obstruct= 1 ,-1
 2107.27 3859.36   30.97
Bank Sta=4980.96,5019.04
XS Rating Curve= 0
Exp/Cntr=.5,.3

Type RM Length L Ch R = 1 ,3602.624,1540.46,1602.99,1655.12
XS GIS Cut Line= 6
     3180550.701    13767907.993     3180924.092    13768353.046
     3181922.809    13769462.556      3182566.13    13770149.069
     3183717.039    13771407.387      3183975.52     13771786.09
#Sta/Elev= 30
 2490.96   30.37 2511.38   29.52 2629.83   30.13  2698.1   29.62 2788.48   28.73
 2945.63   29.59 3005.57   30.74 3376.03   30.49 3516.06   32.11 3620.79    31.1
 3861.08    30.8  4648.4    31.1 4873.61    29.7    4963   28.19  4990.4   22.42
 4994.55   19.83 5005.24    19.7 5009.43   22.19    5027    26.8 5414.73   28.24
 5425.24   29.44 5434.17   29.58 5990.22   31.55 6096.03   32.55 6152.42   31.53
 6217.38   32.38 6354.74   32.66  7207.2   32.76 7416.54    34.1 7669.57   34.57
#Mann= 4 ,-1 , 0
 2490.96     .15       0  2698.1     .07       0    4963    .045       0
    5027     .07       0
#Block Obstruct= 1 ,-1
 2178.78 3916.57   31.03
Bank Sta=4963,5027
XS Rating Curve= 0
Exp/Cntr=.3,.1

Type RM Length L Ch R = 1 ,1999.637,40.73,40.56,95.36
XS GIS Cut Line= 6
     3179798.193    13768891.228       3180677.4    13770235.923
     3180781.497    13770419.227     3180882.201    13770634.572
     3181209.947    13771011.537     3181933.471    13771886.557
#Sta/Elev= 30
 3134.67   32.51 3159.36   34.61 3251.78   34.07  3305.1   28.08 3393.22   30.67
 3429.63    29.8 3474.48   30.26  3549.7   33.68 3584.03   33.93 3598.64   32.67
 3637.31   32.44 3732.86   28.97 3780.94   28.39 3859.57      32 3942.15   32.34
 4013.87   30.68 4169.86    33.6  4220.3   33.71 4262.98   33.44 4340.29   27.48
 4885.95   27.05 4952.15   24.63 4978.51   16.78 4980.54    14.7 5012.66   15.57
 5018.74   18.35 5047.85   25.39 5840.29   30.65 6294.59   32.07 6824.75   31.65
#Mann= 3 ,-1 , 0
 3134.67     .07       0 4952.15    .045       0 5047.85     .07       0
Bank Sta=4952.15,5047.85
XS Rating Curve= 0
Exp/Cntr=.5,.3

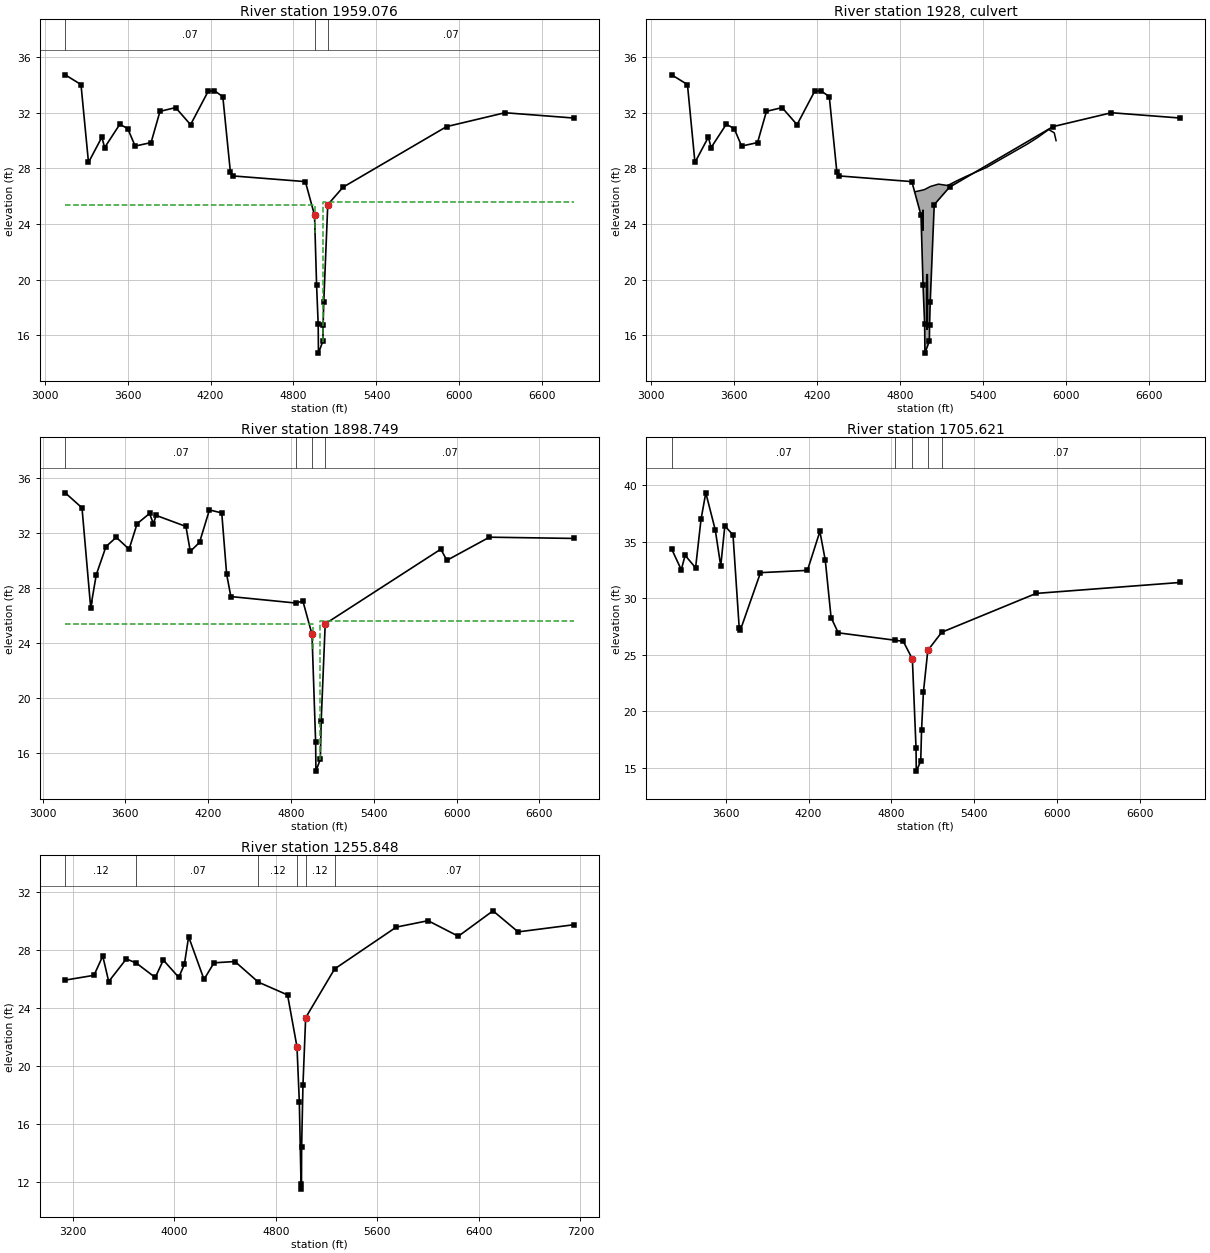
Type RM Length L Ch R = 1 ,1959.076,61.1,60.33,62.01
XS GIS Cut Line= 6
     3179738.893    13768939.746     3180643.003    13770256.354
     3180784.789    13770523.245     3180835.582    13770724.024
     3181158.543    13771081.589     3181866.623    13771907.447
#Sta/Elev= 30
 3148.89   34.74 3263.01   34.04 3317.24   28.43 3414.04   30.25 3434.15    29.5
 3543.76   31.18 3601.13   30.87 3654.66   29.61 3769.87   29.86 3834.27   32.11
 3947.41   32.38 4055.62   31.15 4183.69   33.57  4228.3   33.59 4288.79   33.17
 4343.41   27.75 4360.96   27.46 4885.95   27.05 4952.15   24.63 4967.03   19.59
 4978.51   16.78 4980.54    14.7 5012.66   15.57 5014.27   16.73 5018.74   18.35
 5047.85   25.39 5158.44   26.65 5907.02   31.01  6329.4   32.01 6825.37   31.63
#Mann= 3 ,-1 , 0
 3148.89     .07       0 4952.15    .045       0 5047.85     .07       0
#XS Ineff= 2 , 0
       0    4956    25.4    5010       0    25.6
Permanent Ineff=
       F       F
Bank Sta=4952.15,5047.85
XS Rating Curve= 0
Exp/Cntr=.5,.3

Type RM Length L Ch R = 2 ,1928    ,,,
BEGIN DESCRIPTION:
ACCESS RD OFF BEAMER RD
END DESCRIPTION:
Bridge Culvert--1,0,-1,-1, 0
Deck Dist Width WeirC Skew NumUp NumDn MinLoCord MaxHiCord MaxSubmerge Is_Ogee
19,32,2.6,0, 17, 17, , , .95, 0, 0,0,,
    4908    4959    4978    5020    5078    5146    5205    5279    5357    5424
    5504    5606    5722    5793    5876    5916    5929
   26.32   26.43   26.48    26.7   26.87   26.77   27.08   27.43   27.77   28.06
   28.52    29.1   29.76   30.21    30.8   30.56      30
       0       0       0       0       0       0       0       0       0       0
       0       0       0       0       0       0       0
    4908    4959    4978    5020    5078    5146    5205    5279    5357    5424
    5504    5606    5722    5793    5876    5916    5947
   26.32   26.43   26.48    26.7   26.87   26.77   27.08   27.43   27.77   28.06
   28.52    29.1   29.76   30.21    30.8   30.56      30
       0       0       0       0       0       0       0       0       0       0
       0       0       0       0       0       0       0
Culvert=1,1.5,,32,.0112,.5,1,1,1,23.523,4967,22.86,4967,Culvert #2  , 0 ,19
Culvert Bottom n=.0112
Multiple Barrel Culv=1,4,,32,.012,.5,1,1,1,16.4,16.7, 2,Culvert #1  , 0 ,19
  4993.5  4993.5  4998.5  4998.5
Culvert Bottom n=.012
BC Design=,, 0 ,, 0 ,,,,,,

Type RM Length L Ch R = 1 ,1898.749,164.36,193.13,127.31
XS GIS Cut Line= 6
     3179679.593    13768988.264     3180591.407    13770287.001
      3180730.39    13770548.563     3180752.919      13770704.8
     3181104.716    13771110.424     3181808.131    13771961.761
#Sta/Elev= 30
  3164.3    34.9 3285.94   33.81 3348.83   26.57 3389.38   28.96 3459.75      31
 3534.02   31.67 3626.93   30.81 3685.42   32.66 3775.36    33.4  3802.8   32.66
  3823.3   33.26 4038.83   32.46 4070.49   30.65 4137.24    31.3 4209.03   33.66
 4298.31   33.44 4333.73      29 4364.25   27.37 4835.25    26.9 4885.95   27.05
 4952.15   24.63 4978.51   16.78 4980.54    14.7 5012.66   15.57 5018.74   18.35
 5047.85   25.39 5885.47   30.81 5929.16      30 6237.58   31.68 6846.76   31.59
#Mann= 4 ,-1 , 0
  3164.3     .07       0 4835.25     .12       0 4952.15    .045       0
 5047.85     .07       0
#XS Ineff= 2 , 0
       0    4956    25.4  5010.5       0    25.6
Permanent Ineff=
       F       F
#Block Obstruct= 1 ,-1
    3330    3380    27.1
Bank Sta=4952.15,5047.85
XS Rating Curve= 0
Exp/Cntr=.5,.3

Type RM Length L Ch R = 1 ,1705.621,505.32,449.77,394.01
XS GIS Cut Line= 6
     3179523.257    13769112.255     3180453.818    13770368.727
     3180549.608    13770537.402     3180554.211    13770615.403
     3180662.412    13770777.712     3181728.749    13772041.143
#Sta/Elev= 30
 3207.69   34.37 3277.18   32.54 3305.27   33.81 3381.04   32.71 3420.32   36.99
 3454.95   39.35 3523.54   36.07 3563.25   32.87    3593   36.42 3652.22   35.62
  3697.2   27.37 3705.84    27.2 3851.44   32.28 4191.68   32.48 4281.87   35.93
 4320.97   33.38 4363.01    28.3 4415.14   26.95 4828.69   26.29 4885.95    26.2
 4952.15   24.63 4978.51   16.78 4980.54    14.7 5012.66   15.57 5018.74   18.35
 5032.18   21.69    5064   25.39 5164.75      27 5849.19   30.44 6891.78   31.41
#Mann= 5 ,-1 , 0
 3207.69     .07       0 4828.69     .12       0 4952.15    .045       0
    5064     .12       0 5164.75     .07       0
Bank Sta=4952.15,5064
XS Rating Curve= 0
Exp/Cntr=.3,.1

Type RM Length L Ch R = 1 ,1255.848,856.81,1255.85,901.48
XS GIS Cut Line= 6
     3178822.399    13769367.465     3179956.073    13770496.493
     3180105.457    13770667.637     3180152.559    13770717.101
      3180899.19    13771605.723     3181489.378    13772351.809
#Sta/Elev= 30
 3138.57   25.91 3365.48   26.24 3434.64   27.57 3481.49   25.81 3620.38   27.37
 3699.61   27.08 3848.49   26.09    3912   27.29 4033.85    26.1  4078.2      27
 4111.58    28.9 4232.78   25.96  4311.7    27.1 4476.74   27.19 4661.38   25.77
  4891.5   24.89 4965.85   21.31 4984.37    17.5 4998.55   11.52 5001.17   11.84
 5002.34    14.4  5012.8   18.66 5034.15   23.32 5262.49   26.68  5748.8   29.56
 5999.27      30 6237.71   28.93 6511.23   30.68 6708.94   29.23 7145.96   29.72
#Mann= 6 ,-1 , 0
 3138.57     .12       0 3699.61     .07       0 4661.38     .12       0
 4965.85    .045       0 5034.15     .12       0 5262.49     .07       0
Bank Sta=4965.85,5034.15
XS Rating Curve= 0
Exp/Cntr=.3,.1